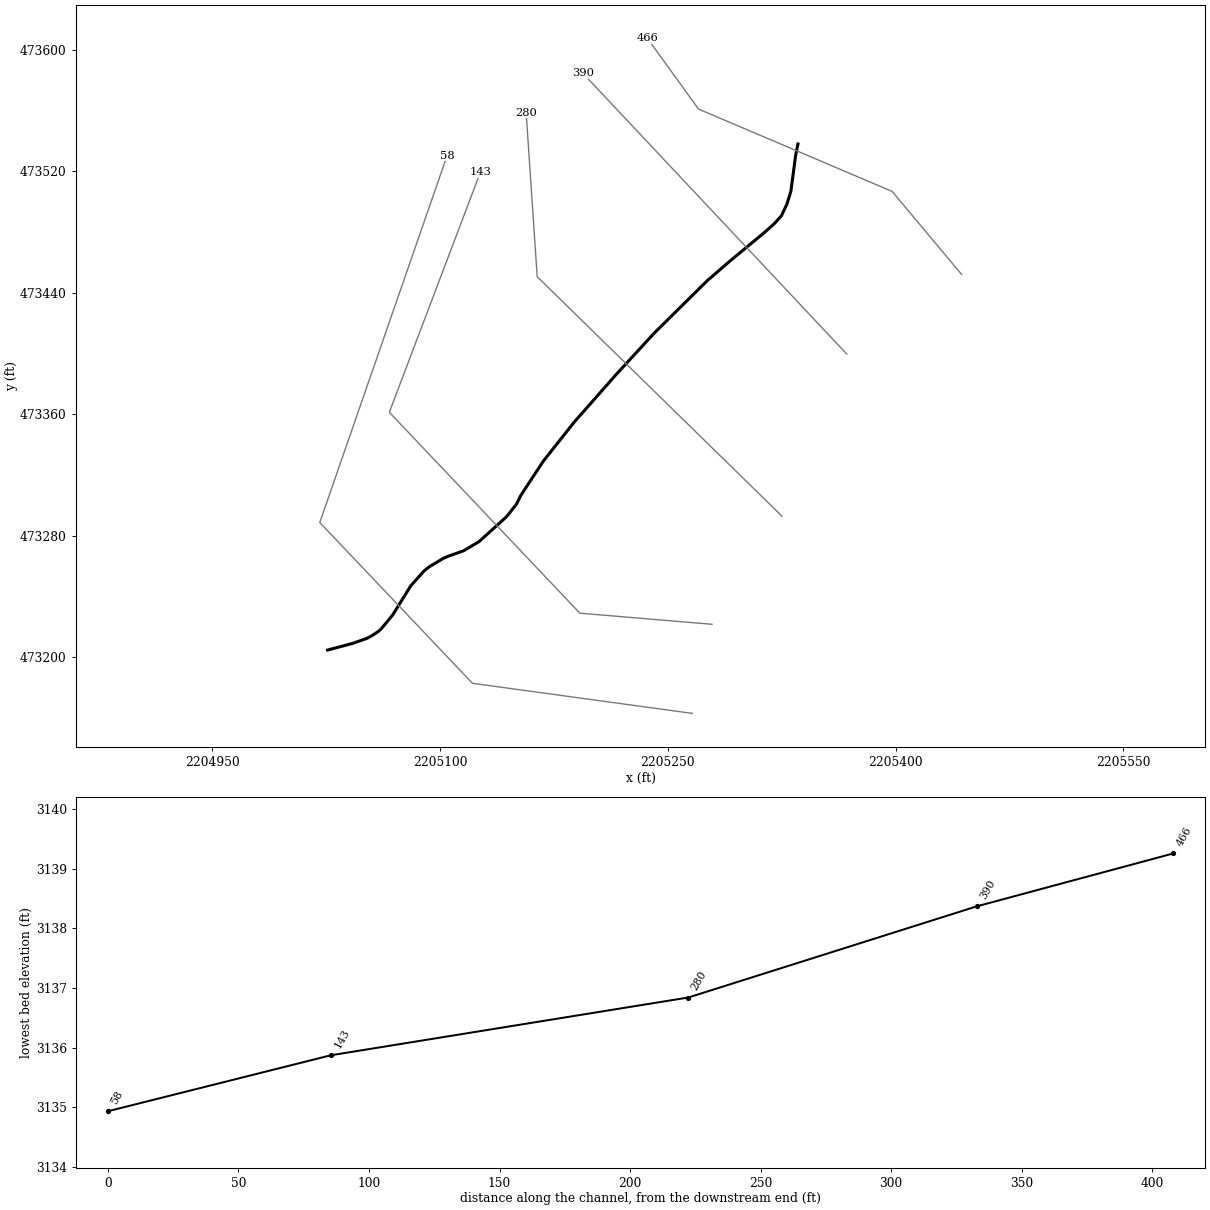
--- FRIELRN.prj (project) ---

Proj Title=FRIELRN
Current Plan=p01
Default Exp/Contr=0,0
English Units
Geom File=g01
Flow File=f01
Plan File=p01
Background Map Layer=Inundation Boundary (01pct Value_0)
BEGIN DESCRIPTION:
----------MODEL BY WOOD PLC 2021----------
Stream Name: Friel Run
Flood Zone: Approximate
Pocahontas County, WV
HEC-RAS Version: RAS 6.1
Vertical Datum: NAVD88
Projection: NAD 1983 StatePlane West Virginia S FIPS 4702 (US Feet)
Terrain: 1-meter LIDAR (FEMA Region III 3DEP collected 2016-2018)
Land Use: 2019 NLCD
Hydrologic Method:
WV SIR2010-5033 regression equations
END DESCRIPTION:
DSS File=dss
DSS Export Rating Curves= 0
DSS Export Rating Curve Sorted= 0
DSS Export Volume Flow Curves= 0
DXF OffsetX= 0
DXF OffsetY= 0
DXF ScaleX= 0
DXF ScaleY= 0

--- FRIELRN.p01 (plan) ---

Plan Title=Floodplain
Program Version=6.00
Short Identifier=Floodplain
Geom File=g01
Flow File=f01
Subcritical Flow
K Sum by GR= 0
Std Step Tol= 0.01
Critical Tol= 0.01
Num of Std Step Trials= 20
Max Error Tol= 0.3
Flow Tol Ratio= 0.001
Split Flow NTrial= 30
Split Flow Tol= 0.02
Split Flow Ratio= 0.02
Log Output Level= 0
Friction Slope Method= 1
Unsteady Friction Slope Method= 2
Unsteady Bridges Friction Slope Method= 1
Parabolic Critical Depth
Global Vel Dist= 0 , 0 , 0
Global Log Level= 0
CheckData=True
Encroach Param=-1 ,0,0, 0
Computation Interval=0.1SEC
Output Interval=1SEC
Instantaneous Interval=Max Profile
Mapping Interval=1HOUR
Computation Time Step Use Courant=        0
Computation Time Step Use Time Series=    0
Computation Time Step Count To Double=0
Computation Time Step Max Doubling=0
Computation Time Step Max Halving=0
Computation Time Step Residence Courant=0
Run HTab= 0
Run UNet= 0
Run Sediment= 0
Run PostProcess= 0
Run WQNet= 0
Run RASMapper=-1
UNET Theta= 0
UNET Theta Warmup= 0
UNET ZTol= 0
UNET ZSATol= 0
UNET MxIter= 0
UNET Max Iter WO Improvement= 0
UNET MaxInSteps= 0
UNET DtIC= 0
UNET DtMin= 0
UNET MaxCRTS= 0
UNET WFStab= 0
UNET SFStab= 0
UNET WFX= 1
UNET SFX= 1
UNET Gravity=32.174
UNET 1D Methodology=Finite Difference
UNET DSS MLevel= 1
UNET Pardiso=0
UNET DZMax Abort= 0
UNET Use Existing IB Tables= 0
UNET Froude Reduction=False
UNET Froude Limit= 0
UNET Froude Power= 0
UNET D1 Cores= 0
UNET WindReference=Eulerian
UNET WindDragFormulation=Hsu (1988)
UNET D2 Coriolis=0
UNET D2 Cores= 0
UNET D2 Theta= 1
UNET D2 Theta Warmup= 1
UNET D2 Z Tol= 0.01
UNET D2 Volume Tol= 0.01
UNET D2 Max Iterations= 20
UNET D2 Equation= 0
UNET D2 RampUpFraction=0.1
UNET D2 TimeSlices= 1
UNET D2 Turbulence Formulation=Non-Conservative (original)
UNET D2 Eddy Viscosity=0.3
UNET D2 Transverse Eddy Viscosity=0.1
UNET D2 Smagorinsky Mixing=0
UNET D2 BCVolumeCheck=0
UNET D2 Cores=0
UNET D2 SolverType=PARDISO (Direct)
UNET D2 Minimum Iterations= 2147483647
UNET D2 Maximum Iterations= 2147483647
UNET D2 Restart Number= 10
UNET D2 Relaxation Coeff=1.3
UNET D2 SOR Precondition Iterations= 10
UNET D2 ILUT Maximum Fill= 8
UNET D2 ILUT Tolerance=1E-08
UNET D1D2 MaxIter= 0
UNET D1D2 ZTol=0.01
UNET D1D2 QTol=0.1
UNET D1D2 MinQTol=1
DSS File=dss
Write IC File= 0
Write IC File at Fixed DateTime=0
Write IC File at Sim End=0
Echo Input=False
Echo Parameters=False
Echo Output=False
Write Detailed= 0
HDF Write Warmup=0
HDF Write Time Slices=0
HDF Flush=0
HDF Compression= 1
HDF Chunk Size= 1
HDF Spatial Parts= 1
HDF Use Max Rows=0
HDF Fixed Rows= 1
Calibration Method= 0
Calibration Iterations= 20
Calibration Max Change=0.05
Calibration Tolerance=0.2
Calibration Maximum=1.5
Calibration Minimum=0.5
Calibration Optimization Method= 1
WQ AD Non Conservative
WQ ULTIMATE=-1
WQ Max Comp Step=1HOUR
WQ Output Interval=15MIN
WQ Output Selected Increments= 0
WQ Output face flow=0
WQ Output face velocity=0
WQ Output face area=0
WQ Output face dispersion=0
WQ Output cell volume=0
WQ Output cell surface area=0
WQ Output cell continuity=0
WQ Output cumulative cell continuity=0
WQ Output face conc=0
WQ Output face dconc_dx=0
WQ Output face courant=0
WQ Output face peclet=0
WQ Output face adv mass=0
WQ Output face disp mass=0
WQ Output cell mass=0
WQ Output cell source sink temp=0
WQ Output nsm pathways=0
WQ Output nsm derived pathways=0
WQ Create Restart=0
WQ Fixed Restart=0
WQ System Summary=0
WQ Write To DSS=0
Sorting and Armoring Iterations= 10
XS Update Threshold= 0.02
Bed Roughness Predictor= 0
Hydraulics Update Threshold= 0.02
Energy Slope Method= 1
Volume Change Method= 1
Sediment Retention Method= 0
Sediment TS Multiplier= 1
Warm Up Method= 0
XS Weighting Method= 0
Number of US Weighted Cross Sections= 1
Number of DS Weighted Cross Sections= 1
Upstream XS Weight=0
Main XS Weight=1
Downstream XS Weight=0
Number of DS XS's Weighted with US Boundary= 1
Upstream Boundary Weight= 1
Weight of XSs Associated with US Boundary= 0
Number of US XS's Weighted with DS Boundary= 1
Downstream Boundary Weight= 0.5
Weight of XSs Associated with DS Boundary= 0.5
Percentile Method= 0
Sediment Output Level= 3
Mass or Volume Output= 0
Output Increment Type= 1
Profile and TS Output Increment= 1
Transport Output Increment 1
XS Output Flag= 0
XS Output Increment= 10
Read HDF5 Sediment Hotstart= 0
Sediment Hotstart Type= 0
Write Gradation File= 0
Read Gradation Hotstart= 0
Write HDF5 File= 1
Write Binary Output= 1
Write DSS Sediment File= 0
DSS Sediment Output Type= 1
SV Curve= 0
Specific Gage Flag= 0
Subcell Erosion Methods= 0
Subcell Deposition Methods= 0
Advection Scheme= 1
Matrix Solver= 0
Implicit Weighting Factor= 1
Maximum Outer Loop Convergence Iterations= 5
Convergence Maximum Absolute= 0.001
Convergence RMSE= 0.0001
Grain Fractions Max Abs Error= 0.001
Max Subgrid Regions= 1
Max Subgrid Length Scale= 3.402823E+38
Initial Layer Thickness= 3.402823E+38
Min Layer Thickness= 3.402823E+38
Max Layer Thickness= 3.402823E+38
Number of Layers= 5

--- FRIELRN.f01 (steady flow) ---

Flow Title=Flow
Program Version=6.00
Number of Profiles= 6
Profile Names=01pct,10pct,04pct,02pct,0_2pct,01plus
River Rch & RM=FRIELRN,Main            ,466
     518     273     364     438     725     767
Boundary for River Rch & Prof#=FRIELRN,Main            , 1
Up Type= 0
Dn Type= 3
Dn Slope=0.01105
Boundary for River Rch & Prof#=FRIELRN,Main            , 2
Up Type= 0
Dn Type= 3
Dn Slope=0.01105
Boundary for River Rch & Prof#=FRIELRN,Main            , 3
Up Type= 0
Dn Type= 3
Dn Slope=0.01105
Boundary for River Rch & Prof#=FRIELRN,Main            , 4
Up Type= 0
Dn Type= 3
Dn Slope=0.01105
Boundary for River Rch & Prof#=FRIELRN,Main            , 5
Up Type= 0
Dn Type= 3
Dn Slope=0.01105
Boundary for River Rch & Prof#=FRIELRN,Main            , 6
Up Type= 0
Dn Type= 3
Dn Slope=0.01105
DSS Import GetInterval= 0
DSS Import GetPeak= 0
DSS Import FillOption= 0

--- FRIELRN.g01 (geometry) ---

Geom Title=Geometry
Program Version=6.10

River Reach=FRIELRN         ,Main
Reach XY= 30
     2205335.733      473537.863     2205334.258      473530.673
     2205331.052       473506.61     2205328.423      473498.172
     2205324.877       473490.64     2205320.456      473485.701
     2205314.165      473480.012     2205290.404       473460.31
     2205275.856      473447.703     2205241.266      473413.503
      2205216.11      473386.185     2205188.206      473354.481
     2205168.011       473328.98     2205153.156      473306.345
     2205150.297       473300.62     2205143.829      473292.409
     2205125.702      473275.992     2205115.405      473269.898
       2205105.8       473266.52     2205102.398      473265.099
     2205092.726      473259.299     2205089.454       473256.64
     2205080.769      473246.935     2205068.786       473227.65
     2205061.359      473218.622     2205059.351      473216.799
     2205055.046      473213.969     2205051.989       473212.32
     2205042.612      473208.991     2205025.936      473204.552

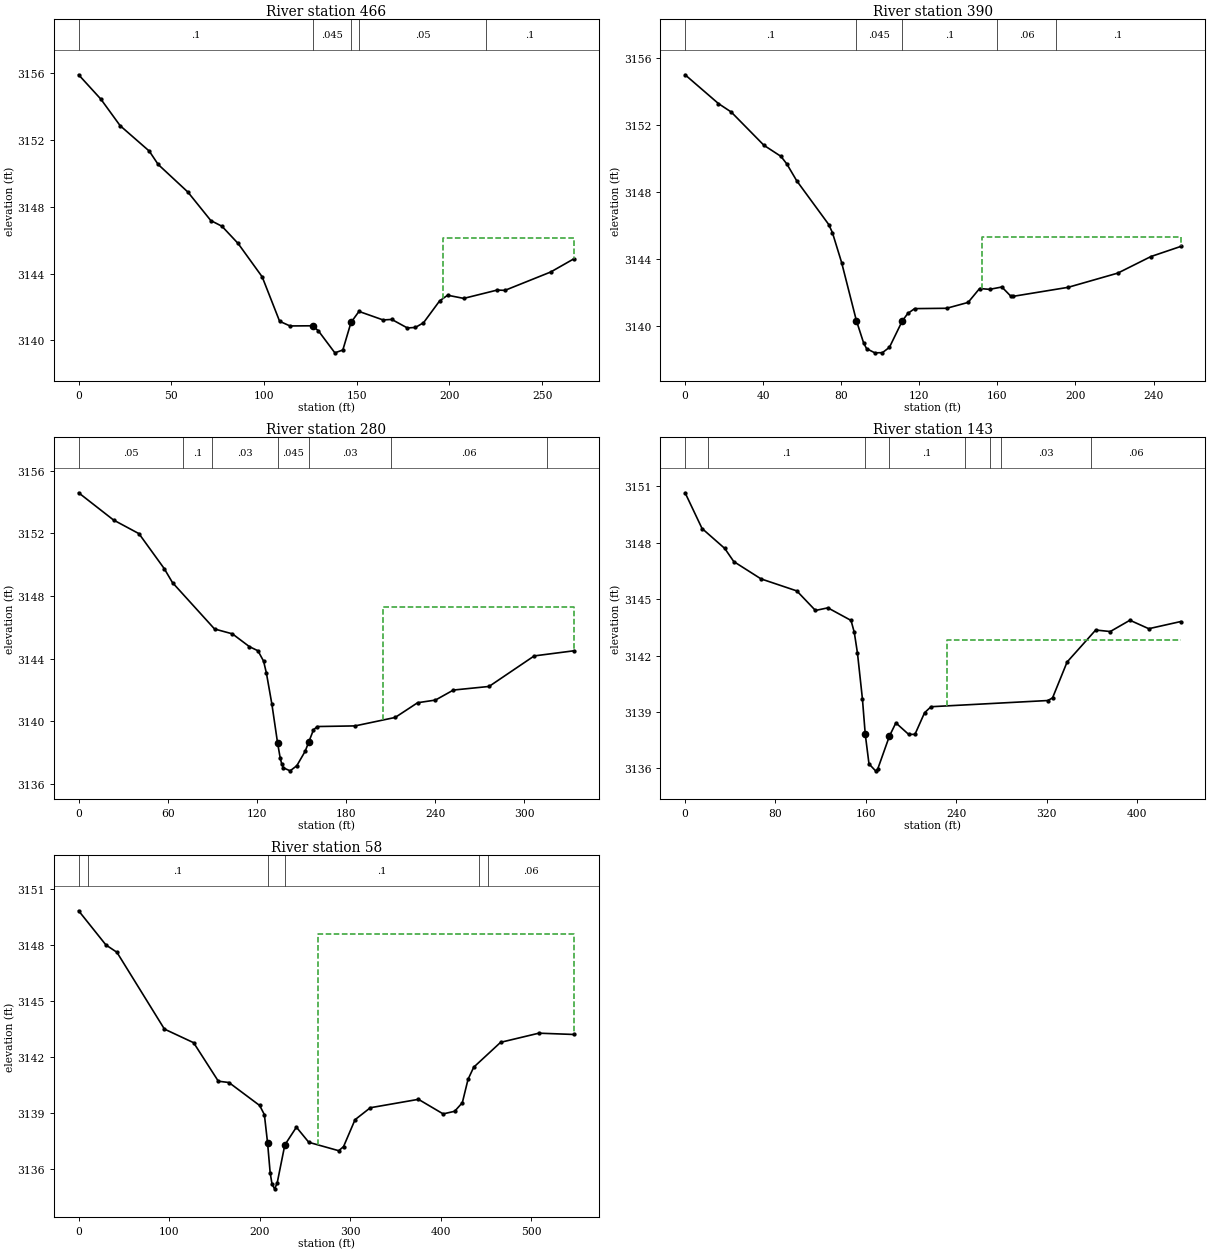
Type RM Length L Ch R = 1 ,466     ,75.4,75.4,75.4
XS GIS Cut Line= 4
2205443.47826029 473451.995902382205397.73231851473506.648133709
2205270.21044541473560.8955336942205236.60944392473607.451138159
#Sta/Elev= 30
       0 3155.91      12 3154.45    22.4 3152.86    38.1 3151.34    42.9 3150.54
    58.9 3148.89    71.3 3147.18    77.3 3146.84      86 3145.81      99 3143.81
   108.4 3141.15     114 3140.87   126.2 3140.88   129.3 3140.58   138.2 3139.26
   142.5 3139.43   146.9 3141.08   151.2 3141.74   164.2 3141.23   168.9 3141.26
   177.3 3140.75   181.6 3140.78     186 3141.06   194.7 3142.37     199 3142.71
   207.7 3142.52   225.8 3143.02   229.9    3143   254.6  3144.1267.2664  3144.9
#Mann= 5 ,-1,0
       0      .1       0   126.2    .045       0   146.9      .1       0
  151.27     .05       0  219.85      .1       0
#XS Ineff= 2 , 0
                          196.31         3146.15
Permanent Ineff=
       F       F
Bank Sta=126.2,146.9
XS Rating Curve= 0 ,0
Exp/Cntr(USF)=0,0
Exp/Cntr=0.3,0.1

Type RM Length L Ch R = 1 ,390     ,110.4,110.4,110.4
XS GIS Cut Line= 2
     2205367.868      473399.5182205193.98711959473584.534238042
#Sta/Elev= 30
       0 3154.97    17.1 3153.25    23.6 3152.75    40.4 3150.76    49.1  3150.1
    52.1 3149.65    57.2 3148.64    73.6 3146.03    75.5 3145.54    80.2 3143.76
   87.75  3140.3    91.5 3138.95      93 3138.62    97.2 3138.37   101.1 3138.38
   104.7  3138.7   111.3 3140.28   114.1 3140.72   117.6 3141.01     134 3141.03
     145 3141.38   150.9 3142.21     156 3142.16   162.3  3142.3     167 3141.74
   167.9 3141.74   196.2 3142.28   221.7 3143.13   238.7 3144.12   253.9 3144.72
#Mann= 5 ,-1,0
       0      .1       0   87.75    .045       0   111.3      .1       0
     160     .06       0     190      .1       0
#XS Ineff= 2 , 0
                          152.07         3145.29
Permanent Ineff=
       F       F
Bank Sta=87.75,111.3
XS Rating Curve= 0 ,0
Exp/Cntr=0.3,0.1

Type RM Length L Ch R = 1 ,280     ,136.9,136.9,136.9
XS GIS Cut Line= 3
      2205325.17      473292.7742205164.00448612473450.440825504
2205156.72637753473558.354914444
#Sta/Elev= 30
       0  3154.6    23.5 3152.86    40.6 3151.99    57.6 3149.76    63.2 3148.86
    91.5  3145.9   103.5 3145.59     115 3144.77   120.7 3144.51   124.5 3143.85
   126.4 3143.09   130.1  3141.1   133.9 3138.64   135.7 3137.66   136.8 3137.25
   137.9 3137.03   142.4 3136.84   146.9 3137.17   152.5 3138.09     155  3138.7
   158.1 3139.46   160.7 3139.67   186.1 3139.71   213.1 3140.25   228.2 3141.19
   240.2 3141.36   252.3    3142   276.3 3142.23   306.7 3144.18   333.6 3144.51
#Mann= 7 ,-1,0
       0     .05       0      70      .1       0      90     .03       0
   133.9    .045       0     155     .03       0     210     .06       0
  315.46     .03       0
#XS Ineff= 2 , 0
                          204.84          3147.3
Permanent Ineff=
       F       F
Bank Sta=133.9,155
XS Rating Curve= 0 ,0
Exp/Cntr=0.3,0.1

Type RM Length L Ch R = 1 ,143     ,85.4,85.4,85.4
XS GIS Cut Line= 4
2205279.13720171473221.5338795572205192.08012377473228.851995481
2205066.61798927473361.1699843262205126.54157147473519.200084074
#Sta/Elev= 30
       0 3150.66      15 3148.76    35.1  3147.7    43.1    3147    67.2 3146.08
    98.9 3145.44   115.4  3144.4   126.4 3144.54   146.9 3143.87   149.8 3143.23
   152.6 3142.13     157 3139.69   159.5 3137.81   162.8 3136.24   168.6 3135.87
   170.5 3135.96   180.9 3137.72   186.6 3138.42   197.9 3137.81   203.5 3137.81
     212 3138.96   217.7 3139.28   321.1 3139.61   325.3 3139.75   338.2 3141.66
   363.5 3143.36   376.4 3143.28   393.8 3143.88   410.5 3143.43   438.7 3143.81
#Mann= 8 ,-1,0
       0     .05       0      20      .1       0   159.5    .045       0
   180.9      .1       0  247.36     .03       0  269.71      .1       0
  279.71     .03       0  359.71     .06       0
#XS Ineff= 2 , 0
                          231.95         3142.85
Permanent Ineff=
       F       F
Bank Sta=159.5,180.9
XS Rating Curve= 0 ,0
Exp/Cntr=0.3,0.1

Type RM Length L Ch R = 1 ,58      ,,,
XS GIS Cut Line= 4
 2205266.0915845 473162.860243782205121.35688168473182.666045219
 2205020.8043513473288.5509067582205104.59812662473530.029331995
#Sta/Elev= 30
       0 3149.81    30.2 3147.98    42.3 3147.59    94.8 3143.48   127.1 3142.75
   154.4 3140.69   166.1 3140.62   200.1 3139.39   205.3  3138.9  208.87 3137.37
   211.7 3135.79   213.8 3135.17   216.6 3134.93   219.4 3135.23   227.9 3137.28
   240.7 3138.23   254.4 3137.42   287.5 3136.97   292.8 3137.19   305.5 3138.63
   322.4 3139.27   375.6 3139.72   402.9 3138.94   415.6 3139.08   424.1 3139.54
   430.4 3140.79   436.7 3141.44   466.4 3142.77   508.7 3143.26547.7092 3143.19
#Mann= 6 ,-1,0
       0     .05       0      10      .1       0  208.87    .045       0
   227.9      .1       0  442.11     .03       0  452.11     .06       0
#XS Ineff= 2 , 0
                          264.52         3148.59
Permanent Ineff=
       F       F
Bank Sta=208.87,227.9
XS Rating Curve= 0 ,0
Exp/Cntr(USF)=0,0
Exp/Cntr=0.3,0.1
LCMann Table=0

Chan Stop Cuts=-1
Use User Specified Reach Order=0
Composite Channel Slope=5